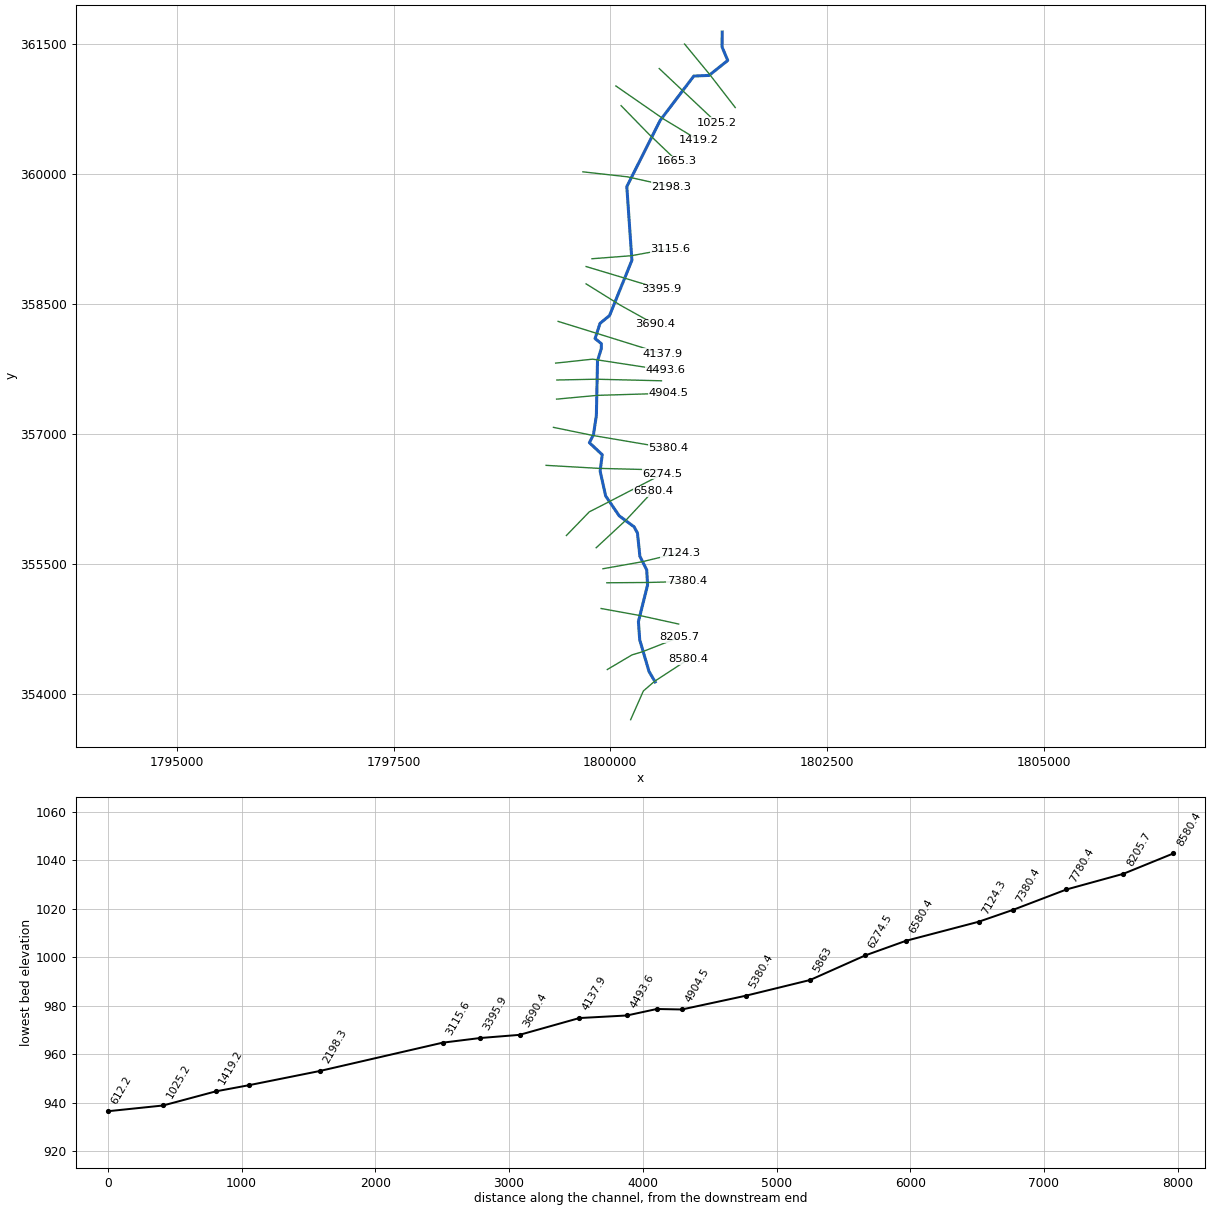
--- ScrtchrsRn.prj (project) ---

Proj Title=ScrtchrsRn
Current Plan=p01
Geom File=g01
Flow File=f01
Plan File=p01
DSS Export Rating Curves=0
DSS Export Rating Curve Sorted=0
DSS Export Volume Flow Curves=0
DXF OffsetX=0
DXF OffsetY=0
DXF ScaleX=0
DXF ScaleY=0

--- ScrtchrsRn.p01 (plan) ---

Plan Title=Floodplain
Program Version=4.00
Geom File=g01
Flow File=f01
K Sum by GR=0
Std Step Tol=0.01
Critical Tol=0.01
Num of Std Step Trials=20
Max Error Tol=0.3
Flow Tol Ratio=0.001
Split Flow NTrial=30
Split Flow Tol=0.02
Split Flow Ratio=0.02
Log Output Level=0
Friction Slope Method=1
Unsteady Friction Slope Method=2
Unsteady Bridges Friction Slope Method=1
Global Log Level=0
CheckData=False
Run HTab=0
Run UNet=0
Run PostProcess=0
UNET Theta=0
UNET Theta Warmup=0
UNET ZTol=0
UNET ZSATol=0
UNET MxIter=0
UNET MaxInSteps=0
UNET DtIC=0
UNET DtMin=0
UNET MaxCRTS=0
UNET WFStab=0
UNET SFStab=0
UNET WFX=0
UNET SFX=0
UNET DSS MLevel=0
UNET DZMax Abort=0
UNET Convert EG Bridges=0
UNET Use Existing IB Tables=0
UNET Froude Limit=0
UNET Froude Power=0
Write IC File=0
Echo Input=False
Echo Output=False
Write Detailed=0

--- ScrtchrsRn.f01 (steady flow) ---

Flow Title=NFF Regression Equation
Program Version=4.00
Number of Profiles=1
Profile Names=P100yr
River Rch & RM=ScrtchrsRn,Main      ,8580.4
747.4272
River Rch & RM=ScrtchrsRn,Main      ,7780.4
816.4711
River Rch & RM=ScrtchrsRn,Main      ,5863
866.6811
River Rch & RM=ScrtchrsRn,Main      ,5380.4
1020.309
River Rch & RM=ScrtchrsRn,Main      ,3690.4
1096.266
River Rch & RM=ScrtchrsRn,Main      ,612.2
1202.394
Boundary for River Rch & Prof#=ScrtchrsRn,Main      ,1
Up Type=0
Dn Type=3
Dn Slope=0.010738

--- ScrtchrsRn.g01 (geometry) ---

Geom Title=USGS 3m DEM
Program Version=4.00

River Reach=ScrtchrsRn     ,Main
Reach XY= 30
     1800517.567      354141.237     1800446.102      354261.599
     1800338.905      354626.445     1800323.860      354837.078
     1800429.176      355258.344     1800419.773      355433.244
     1800340.785      355591.219     1800312.576      355860.152
     1800273.082      355931.617     1800101.943      356057.621
     1799945.849      356287.060     1799881.907      356574.800
     1799906.355      356762.865     1799757.784      356902.033
     1799804.800      356992.304     1799838.652      357216.102
     1799851.816      357846.120     1799895.071      357985.288
     1799896.952      358043.588     1799823.627      358102.969
     1799880.881      358278.069     1799990.588      358368.590
     1800248.634      359006.481     1800189.853      359856.799
     1800575.864      360622.052     1800962.564      361131.762
     1801138.474      361139.598     1801354.456      361312.160
     1801288.633      361468.254     1801290.934      361640.178

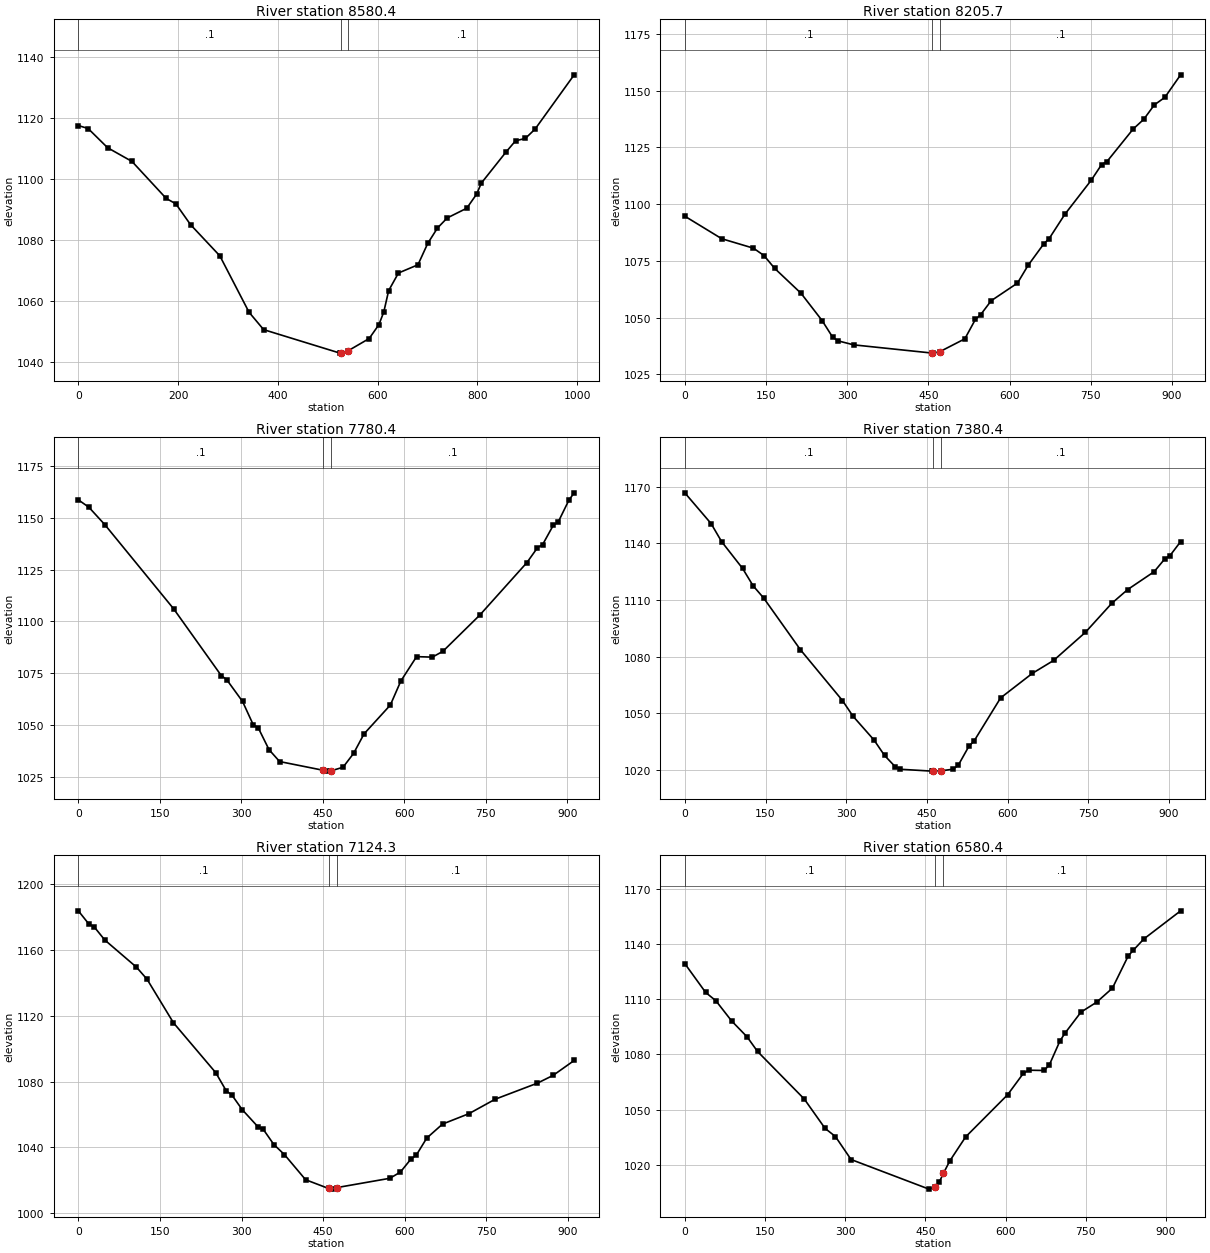
Type RM Length L Ch R = 1 ,8580.4,383.136,374.746,370.061
XS GIS Cut Line= 4
     1800234.271      353705.346     1800380.586      354036.353
     1800511.037      354148.811     1800896.184      354400.211
#Sta/Elev= 30
       0 1117.53    19.6 1116.55    58.7 1110.24   107.6 1105.73   176.1 1093.60
   195.6 1091.79   225.0 1084.96   283.7 1074.72   342.3 1056.18   371.5 1050.48
   524.6 1042.76   526.6 1042.80   541.6 1043.60   583.1 1047.55   602.6 1052.10
   612.4 1056.28   622.2 1063.31   641.8 1069.08   680.9 1071.78   700.5 1078.80
   720.1 1083.87   739.6 1087.17   778.8 1090.37   798.4 1094.96   808.1 1098.64
   857.1 1108.75   876.6 1112.52   896.2 1113.29   915.8 1116.37   994.1 1134.19
#Mann= 3 , 0 , 0
       0     0.1       0   526.6   0.045       0   541.6     0.1       0
Bank Sta=   526.6,   541.6
Exp/Cntr=0.3,0.1

Type RM Length L Ch R = 1 ,8205.7,437.119,425.254,411.846
XS GIS Cut Line= 4
     1799964.843      354284.148     1800250.201      354453.368
     1800363.003      354486.696     1800797.611      354656.797
#Sta/Elev= 30
       0 1094.67    68.3 1084.73   126.8 1080.58   146.4 1077.32   165.9 1071.71
   214.7 1060.72   253.7 1048.69   273.2 1041.36   283.0 1039.76   312.2 1037.99
   456.7 1034.38   459.1 1034.35   471.7 1035.05   517.4 1040.65   536.9 1049.19
   546.6 1051.28   566.1 1057.43   614.7 1065.21   634.1 1072.95   663.3 1082.49
   673.0 1084.73   702.2 1095.50   750.8 1110.47   770.2 1117.43   780.0 1118.73
   828.6 1133.11   848.0 1137.33   867.5 1143.69   886.9 1146.98   916.1 1156.93
#Mann= 3 , 0 , 0
       0     0.1       0   456.7   0.045       0   471.7     0.1       0
Bank Sta=   456.7,   471.7
Exp/Cntr=0.3,0.1

Type RM Length L Ch R = 1 ,7780.4,396.279,400,404.986
XS GIS Cut Line= 3
     1799893.542      354988.291     1800344.522      354906.578
     1800788.422      354808.870
#Sta/Elev= 30
       0 1158.59    19.5 1154.99    48.8 1146.62   175.5 1106.07   263.3 1073.87
   273.0 1072.01   302.3 1061.47   321.8 1050.35   331.6 1048.55   351.1 1038.22
   370.6 1032.51   450.8 1028.31   458.3 1027.90   465.8 1028.09   487.3 1029.77
   506.7 1036.42   526.0 1045.85   574.4 1059.73   593.7 1071.30   622.7 1083.05
   651.7 1082.81   671.1 1085.60   738.8 1102.99   825.8 1128.35   845.2 1135.49
   854.8 1137.06   874.2 1146.25   883.8 1148.11   903.2 1158.47   912.8 1161.96
#Mann= 3 , 0 , 0
       0     0.1       0   450.8   0.045       0   465.8     0.1       0
Bank Sta=   450.8,   465.8
Exp/Cntr=0.3,0.1

Type RM Length L Ch R = 1 ,7380.4,251.571,256.072,260.876
XS GIS Cut Line= 3
     1799959.565      355285.166     1800428.401      355288.569
     1800880.809      355300.169
#Sta/Elev= 30
       0 1166.77    48.8 1150.52    68.4 1140.96   107.4 1126.75   127.0 1117.55
   146.5 1111.13   214.9 1083.72   293.0 1056.83   312.6 1048.55   351.6 1035.96
   371.2 1027.78   390.7 1021.93   400.5 1020.48   459.1 1019.49   461.3 1019.49
   476.3 1019.66   498.4 1020.50   508.2 1022.62   527.9 1032.62   537.7 1035.49
   586.9 1058.25   645.9 1071.24   685.3 1078.05   744.3 1092.91   793.5 1108.31
   823.0 1115.58   872.2 1125.03   891.9 1131.78   901.7 1133.57   921.4 1140.95
#Mann= 3 , 0 , 0
       0     0.1       0   461.3   0.045       0   476.3     0.1       0
Bank Sta=   461.3,   476.3
Exp/Cntr=0.3,0.1

Type RM Length L Ch R = 1 ,7124.3,531.658,543.928,557.101
XS GIS Cut Line= 3
     1799914.679      355447.072     1800364.181      355527.093
     1800806.157      355634.224
#Sta/Elev= 30
       0 1183.89    19.4 1175.84    29.1 1174.13    48.6 1166.15   106.9 1149.60
   126.3 1142.27   174.9 1115.76   252.6 1085.43   272.0 1074.31   281.7 1072.10
   301.1 1063.00   330.3 1052.47   340.0 1050.92   359.4 1041.73   378.9 1035.58
   417.7 1020.33     460 1015.00   466.2 1014.61     475 1015.53   572.7 1021.21
   592.0 1025.01   611.4 1032.94   621.1 1035.26   640.4 1045.67   669.4 1054.18
   717.8 1060.49   766.2 1069.31   843.6 1079.05   872.6 1083.79   911.3 1092.86
#Mann= 3 , 0 , 0
       0     0.1       0     460   0.045       0     475     0.1       0
Bank Sta=     460,     475
Exp/Cntr=0.3,0.1

Type RM Length L Ch R = 1 ,6580.4,311.875,305.95,298.506
XS GIS Cut Line= 3
     1799836.557      355689.300     1800185.633      356013.236
     1800493.531      356343.129
#Sta/Elev= 30
       0 1129.35    38.9 1113.71    58.3 1109.10    87.5 1098.21   116.6 1089.49
   136.1 1081.58   223.5 1055.73   262.4 1039.77   281.8 1035.33   311.0 1022.85
   456.8 1006.75   468.7 1008.17   476.2 1010.71   483.7 1015.30   495.8 1022.12
   525.3 1035.13   603.8 1058.04   633.2 1069.64   643.0 1071.40   672.4 1071.24
   682.2 1074.45   701.9 1087.41   711.7 1091.72   741.1 1102.98   770.5 1108.40
   799.9 1116.00   829.4 1133.47   839.2 1136.69   858.8 1142.77   927.5 1158.04
#Mann= 3 , 0 , 0
       0     0.1       0   468.7   0.045       0   483.7     0.1       0
Bank Sta=   468.7,   483.7
Exp/Cntr=0.3,0.1

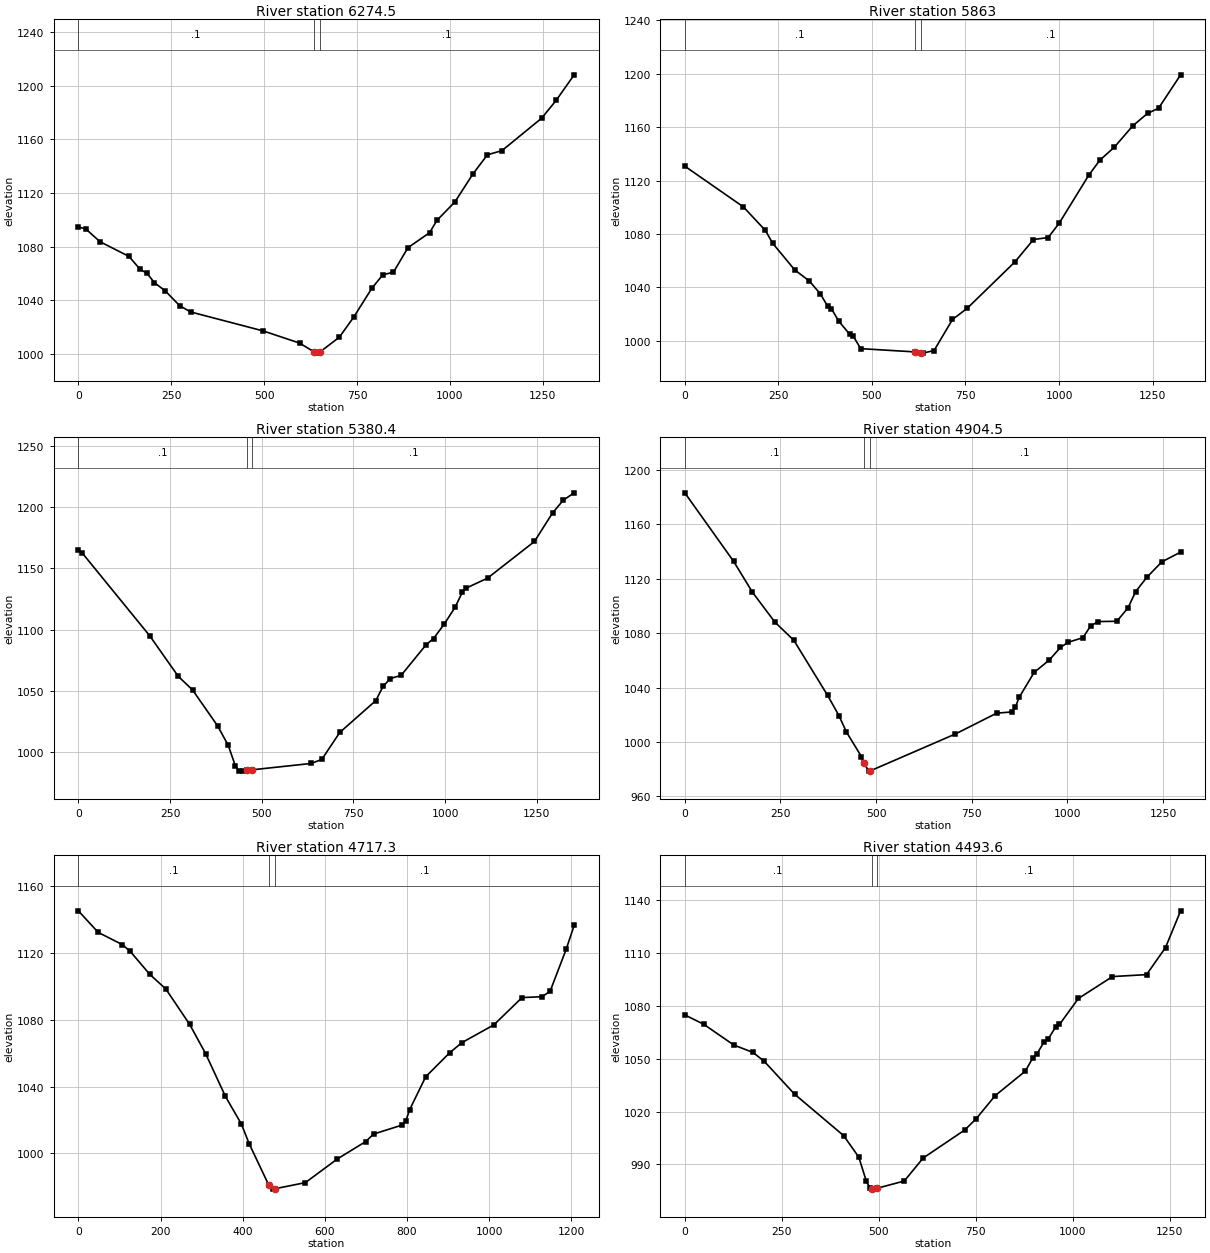
Type RM Length L Ch R = 1 ,6274.5,423.09,411.438,399.901
XS GIS Cut Line= 4
     1799493.005      355830.811     1799757.252      356103.760
     1799983.717      356219.383     1800604.903      356541.820
#Sta/Elev= 30
       0 1094.57    19.5 1093.39    58.4 1083.70   136.4 1072.76   165.6 1063.31
   185.1 1060.09   204.6 1053.22   233.8 1047.09   272.8 1036.01   302.0 1031.40
   497.3 1017.24   595.1 1008.21   634.5 1001.62   643.9 1000.70   649.5 1001.43
   702.2 1012.54   741.1 1027.57   789.7 1048.99   818.9 1058.96   848.0 1061.06
   886.9 1079.26   945.2 1090.45   964.7 1099.58  1013.3 1113.39  1061.9 1134.29
  1100.8 1148.50  1139.7 1151.56  1246.6 1175.76  1285.5 1188.97  1334.1 1208.07
#Mann= 3 , 0 , 0
       0     0.1       0   634.5   0.045       0   649.5     0.1       0
Bank Sta=   634.5,   649.5
Exp/Cntr=0.3,0.1

Type RM Length L Ch R = 1 ,5863,481.843,482.612,479.546
XS GIS Cut Line= 3
     1799258.523      356640.151     1799864.617      356605.458
     1800582.211      356587.204
#Sta/Elev= 30
       0 1130.75   156.7 1100.18   215.4 1082.54   235.0 1072.86   293.8 1052.95
   332.9 1044.64   362.3 1034.96   381.9 1025.67   391.7 1023.91   411.3 1014.60
   440.6 1004.73   450.4 1003.22   470.0  993.95   615.4  991.50   630.4  990.66
   636.6  990.59   666.1  992.55   715.3 1015.81   754.6 1024.19   882.4 1059.05
   931.6 1075.74   970.9 1077.23  1000.4 1087.97  1079.1 1123.81  1108.6 1135.11
  1147.9 1145.02  1197.1 1161.00  1236.4 1170.28  1265.9 1174.16  1324.9 1199.22
#Mann= 3 , 0 , 0
       0     0.1       0   615.4   0.045       0   630.4     0.1       0
Bank Sta=   615.4,   630.4
Exp/Cntr=0.3,0.1

Type RM Length L Ch R = 1 ,5380.4,469.601,475.915,480.237
XS GIS Cut Line= 3
     1799343.403      357078.502     1799800.890      356984.485
     1800672.979      356836.814
#Sta/Elev= 30
       0 1164.75     9.7 1162.99   194.6 1094.87   272.4 1061.67   311.4 1050.53
   379.5 1021.20   408.7 1005.17   428.1  988.37   437.9  984.42   447.6  984.09
   459.5  984.65   474.5  985.19   634.1  990.35   663.6  993.64   712.7 1015.75
   811.0 1041.86   830.7 1053.42   850.3 1059.89   879.8 1062.45   948.6 1087.74
   968.3 1092.65   997.7 1104.54  1027.2 1118.30  1046.9 1130.67  1056.7 1133.83
  1115.7 1142.11  1243.4 1172.09  1292.6 1195.41  1322.1 1205.93  1351.6 1211.91
#Mann= 3 , 0 , 0
       0     0.1       0   459.5   0.045       0   474.5     0.1       0
Bank Sta=   459.5,   474.5
Exp/Cntr=0.3,0.1

Type RM Length L Ch R = 1 ,4904.5,189.347,187.211,185.888
XS GIS Cut Line= 3
     1799379.546      357404.108     1799848.955      357447.641
     1800672.979      357472.184
#Sta/Elev= 30
       0 1183.30   127.7 1132.81   176.8 1110.12   235.7 1088.05   284.8 1074.80
   373.2 1034.21   402.7 1019.39   422.3 1007.30   461.6  989.18   468.5  984.07
   481.2  978.45   483.5  978.50   707.0 1005.77   814.9 1021.08   854.2 1022.03
   864.0 1025.59   873.8 1032.75   913.1 1051.13   952.3 1060.16   981.8 1069.49
  1001.4 1073.23  1040.6 1076.71  1060.3 1085.18  1079.9 1088.54  1129.0 1088.75
  1158.4 1098.64  1178.0 1110.48  1207.5 1121.14  1246.7 1132.49  1295.8 1139.69
#Mann= 3 , 0 , 0
       0     0.1       0   468.5   0.045       0   483.5     0.1       0
Bank Sta=   468.5,   483.5
Exp/Cntr=0.3,0.1

Type RM Length L Ch R = 1 ,4717.3,226.797,223.683,220.896
XS GIS Cut Line= 3
     1799383.356      357625.026     1799838.179      357633.944
     1800589.775      357615.899
#Sta/Elev= 30
       0 1145.18    48.4 1132.28   106.5 1125.03   125.8 1121.04   174.2 1107.08
   212.9 1098.42   271.0 1077.21   309.7 1059.77   358.1 1034.08   396.8 1017.60
   416.2 1005.59   463.5  981.04   474.4  978.65   478.5  978.89   552.5  982.53
   630.7  996.76   699.0 1007.05   718.5 1011.59   786.9 1016.91   796.6 1019.22
   806.4 1026.24   845.5 1045.91   904.0 1060.32   933.3 1066.27  1011.4 1076.96
  1079.8 1093.27  1128.6 1093.80  1148.1 1097.01  1187.2 1122.11  1206.7 1136.49
#Mann= 3 , 0 , 0
       0     0.1       0   463.5   0.045       0   478.5     0.1       0
Bank Sta=   463.5,   478.5
Exp/Cntr=0.3,0.1

Type RM Length L Ch R = 1 ,4493.6,354.707,355.662,354.643
XS GIS Cut Line= 3
     1799368.800      357819.656     1799795.563      357865.508
     1800635.159      357736.921
#Sta/Elev= 30
       0 1074.95    48.8 1069.62   126.8 1057.77   175.6 1053.66   204.9 1048.57
   282.9 1029.96   409.7 1006.35   448.7  994.14   468.3  980.35   478.0  976.50
   481.9  976.29   487.8  975.98   496.9  976.53   565.9  980.59   614.7  993.65
   722.1 1009.61   751.4 1015.95   800.2 1029.05   878.3 1043.03   897.8 1050.70
   907.6 1052.62   927.1 1059.82   936.9 1061.14   956.4 1068.15   966.2 1069.52
  1015.0 1084.27  1102.9 1096.72  1190.7 1097.82  1239.6 1113.18  1278.6 1134.06
#Mann= 3 , 0 , 0
       0     0.1       0   481.9   0.045       0   496.9     0.1       0
Bank Sta=   481.9,   496.9
Exp/Cntr=0.3,0.1

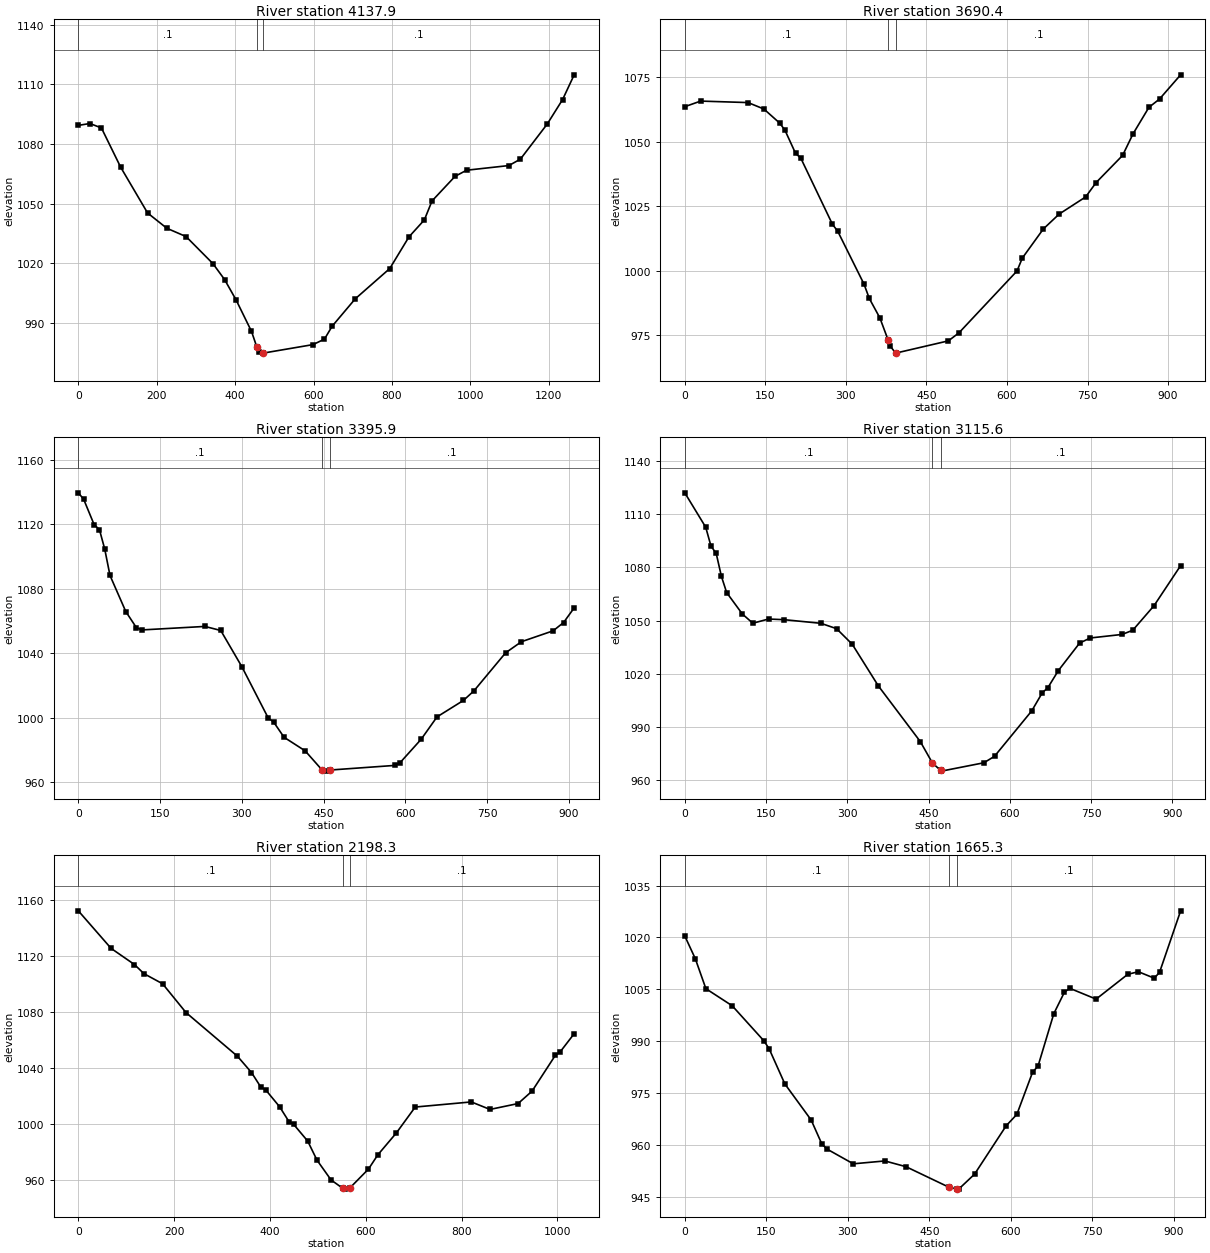
Type RM Length L Ch R = 1 ,4137.9,453.937,447.531,441.056
XS GIS Cut Line= 3
     1799396.865      358301.414     1799847.024      358161.989
     1800604.903      357926.020
#Sta/Elev= 30
       0 1089.37    29.5 1090.31    58.9 1088.09   108.0 1068.36   176.7 1045.35
   225.8 1037.67   274.9 1033.49   343.6 1019.85   373.1 1011.91   402.5 1001.65
   441.8  985.84   455.2  978.10   461.4  975.43   470.2  974.97   471.3  974.92
   598.7  979.20   628.0  981.97   647.6  988.46   706.4 1002.19   794.6 1017.44
   843.6 1033.36   882.8 1041.87   902.4 1051.41   961.2 1063.77   990.6 1066.84
  1098.4 1069.18  1127.8 1072.40  1196.4 1090.08  1235.6 1102.38  1265.0 1114.78
#Mann= 3 , 0 , 0
       0     0.1       0   455.2   0.045       0   470.2     0.1       0
Bank Sta=   455.2,   470.2
Exp/Cntr=0.3,0.1

Type RM Length L Ch R = 1 ,3690.4,288.555,294.539,300.425
XS GIS Cut Line= 3
     1799720.245      358734.187     1800120.317      358485.139
     1800515.550      358265.564
#Sta/Elev= 30
       0 1063.63    29.5 1065.80   117.8 1065.22   147.3 1062.72   176.7 1057.26
   186.5 1054.51   206.2 1045.55   216.0 1043.67   274.9 1018.01   284.7 1015.33
   333.8  994.75   343.6  989.21   363.3  981.66   378.5  973.16   382.9  970.64
   392.7  967.99   393.5  968.03   490.9  972.75   510.6  975.87   618.7  999.87
   628.5 1004.85   667.8 1016.19   697.3 1021.97   746.5 1028.60   766.1 1034.20
   815.3 1044.71   834.9 1053.13   864.4 1063.38   884.1 1066.60   923.4 1075.99
#Mann= 3 , 0 , 0
       0     0.1       0   378.5   0.045       0   393.5     0.1       0
Bank Sta=   378.5,   393.5
Exp/Cntr=0.3,0.1

Type RM Length L Ch R = 1 ,3395.9,270.678,280.278,291.262
XS GIS Cut Line= 3
     1799719.836      358934.116     1800155.610      358803.230
     1800590.806      358670.459
#Sta/Elev= 30
       0 1139.62     9.7 1135.69    29.0 1119.85    38.7 1116.80    48.4 1104.74
    58.1 1088.28    87.1 1065.85   106.5 1055.87   116.2 1054.42   232.3 1056.60
   261.4 1054.08   300.1 1031.59   348.5  999.71   358.2  997.29   377.6  987.72
   416.3  979.29   447.5  967.34   455.0  966.69   462.5  967.38   580.9  970.24
   590.5  971.94   629.3  986.53   658.3 1000.39   706.7 1010.61   726.1 1016.58
   784.2 1040.21   813.2 1047.10   871.3 1053.86   890.6 1059.03   910.0 1068.13
#Mann= 3 , 0 , 0
       0     0.1       0   447.5   0.045       0   462.5     0.1       0
Bank Sta=   447.5,   462.5
Exp/Cntr=0.3,0.1

Type RM Length L Ch R = 1 ,3115.6,925.119,917.254,908.103
XS GIS Cut Line= 3
     1799788.092      359024.071     1800240.803      359058.916
     1800694.667      359141.527
#Sta/Elev= 30
       0 1122.25    38.6 1102.80    48.3 1092.16    58.0 1087.94    67.6 1074.97
    77.3 1065.80   106.3 1053.67   125.6 1048.46   154.6 1050.84   183.6 1050.46
   251.2 1048.42   280.2 1045.38   309.1 1036.58   357.4 1012.96   434.7  981.53
   457.3  969.31   472.3  965.21   473.7  964.77   552.2  969.50   571.8  973.16
   640.5  998.85   660.2 1009.22   670.0 1011.84   689.6 1021.64   728.9 1037.23
   748.5 1040.11   807.4 1042.12   827.0 1044.48   866.3 1058.39   915.4 1081.06
#Mann= 3 , 0 , 0
       0     0.1       0   457.3   0.045       0   472.3     0.1       0
Bank Sta=   457.3,   472.3
Exp/Cntr=0.3,0.1

Type RM Length L Ch R = 1 ,2198.3,545.547,533.084,520.011
XS GIS Cut Line= 3
     1799683.182      360026.946     1800197.789      359969.181
     1800702.717      359857.023
#Sta/Elev= 30
       0 1152.40    68.4 1125.51   117.2 1113.94   136.8 1107.45   175.9 1100.17
   224.7 1079.58   332.2 1048.27   361.5 1036.62   381.1 1026.11   390.8 1024.33
   420.1 1012.15   439.7 1001.48   449.4  999.54   478.8  987.55   498.3  973.84
   527.6  959.70     552  953.71   556.9  953.12     567  954.01   605.7  967.47
   625.2  977.66   664.2  993.47   703.3 1011.90   820.4 1015.56   859.4 1010.19
   918.0 1014.39   947.2 1023.28   996.0 1049.02  1005.8 1051.36  1035.1 1064.40
#Mann= 3 , 0 , 0
       0     0.1       0     552   0.045       0     567     0.1       0
Bank Sta=     552,     567
Exp/Cntr=0.3,0.1

Type RM Length L Ch R = 1 ,1665.3,242.363,246.04,250.419
XS GIS Cut Line= 3
     1800123.844      360790.688     1800441.709      360464.653
     1800771.954      360148.909
#Sta/Elev= 30
       0 1020.43    19.4 1013.83    38.8 1005.19    87.2 1000.25   145.3  990.15
   155.0  987.87   184.1  977.64   232.5  967.21   251.9  960.36   261.6  958.81
   310.0  954.55   368.1  955.38   406.9  953.72   485.6  947.81   500.6  947.28
   503.9  947.23   533.1  951.56   591.4  965.58   610.9  968.84   640.0  981.10
   649.8  982.78   678.9  997.97   698.4 1004.17   708.1 1005.31   756.7 1002.17
   815.0 1009.35   834.5 1010.09   863.6 1008.23   873.4 1009.90   912.2 1027.70
#Mann= 3 , 0 , 0
       0     0.1       0   485.6   0.045       0   500.6     0.1       0
Bank Sta=   485.6,   500.6
Exp/Cntr=0.3,0.1

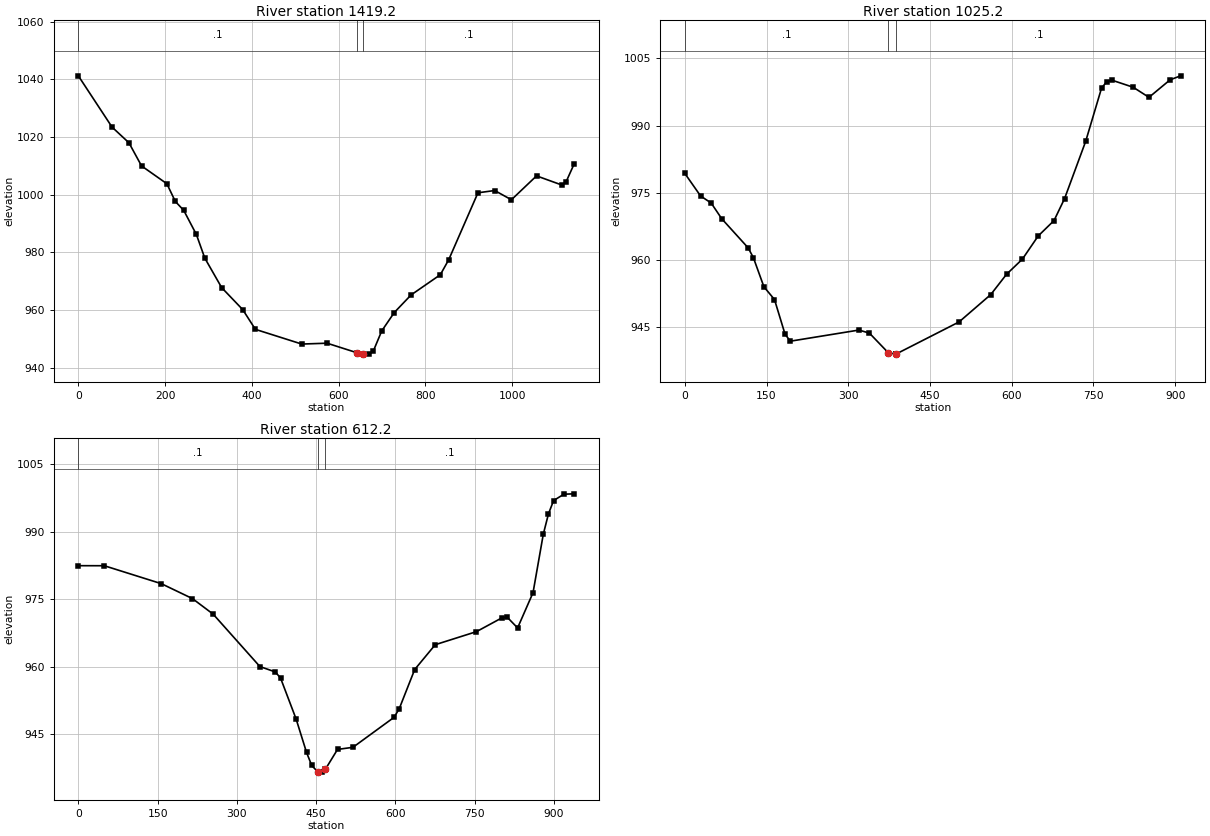
Type RM Length L Ch R = 1 ,1419.2,397.433,394.057,390.589
XS GIS Cut Line= 3
     1800063.923      361017.605     1800614.878      360635.827
     1801019.134      360391.526
#Sta/Elev= 30
       0 1041.20    77.7 1023.42   116.6 1017.99   145.7 1009.96   204.0 1003.79
   223.4  997.67   242.9  994.55   272.0  986.20   291.4  978.01   330.3  967.77
   378.9  960.13   408.0  953.30   514.9  948.20   573.2  948.50   641.7  945.21
   656.7  944.86   670.3  944.71   679.9  945.82   699.2  952.76   728.1  959.14
   766.7  965.22   834.2  972.24   853.5  977.43   920.9 1000.65   959.5 1001.43
   998.0  998.23  1055.9 1006.51  1113.7 1003.37  1123.4 1004.25  1142.6 1010.66
#Mann= 3 , 0 , 0
       0     0.1       0   641.7   0.045       0   656.7     0.1       0
Bank Sta=   641.7,   656.7
Exp/Cntr=0.3,0.1

Type RM Length L Ch R = 1 ,1025.2,424.661,412.99,409.032
XS GIS Cut Line= 3
     1800563.891      361218.707     1800895.034      360906.668
     1801226.178      360594.628
#Sta/Elev= 30
       0  979.30    29.0  974.25    48.4  972.67    67.8  969.16   116.2  962.66
   125.9  960.45   145.2  953.94   164.6  951.10   183.9  943.38   193.6  941.78
   319.5  944.27   338.8  943.59   373.2  939.23   387.2  938.89   388.2  938.94
   503.4  946.09   561.5  952.20   590.5  956.74   619.6  960.13   648.6  965.31
   677.7  968.76   697.0  973.66   735.7  986.45   764.8  998.34   774.5  999.84
   784.1 1000.13   822.9  998.56   851.9  996.30   890.6 1000.21   910.0 1001.11
#Mann= 3 , 0 , 0
       0     0.1       0   373.2   0.045       0   388.2     0.1       0
Bank Sta=   373.2,   388.2
Exp/Cntr=0.3,0.1

Type RM Length L Ch R = 1 ,612.2,584.827,612.175,639.298
XS GIS Cut Line= 3
     1800856.066      361502.081     1801149.375      361146.155
     1801441.036      360768.808
#Sta/Elev= 30
       0  982.43    49.1  982.42   157.0  978.43   215.9  975.11   255.1  971.65
   343.5  960.00   372.9  958.79   382.7  957.41   412.1  948.31   431.8  940.89
   441.6  938.00   452.6  936.63   461.2  936.52   467.6  937.19   490.4  941.57
   519.6  942.04   597.5  948.72   607.2  950.64   636.4  959.34   675.3  964.86
   753.2  967.76   801.9  970.86   811.6  970.95   831.1  968.59   860.3  976.43
   879.7  989.42   889.5  993.96   899.2  996.91   918.7  998.33   938.1  998.41
#Mann= 3 , 0 , 0
       0     0.1       0   452.6   0.045       0   467.6     0.1       0
Bank Sta=   452.6,   467.6
Exp/Cntr=0.3,0.1